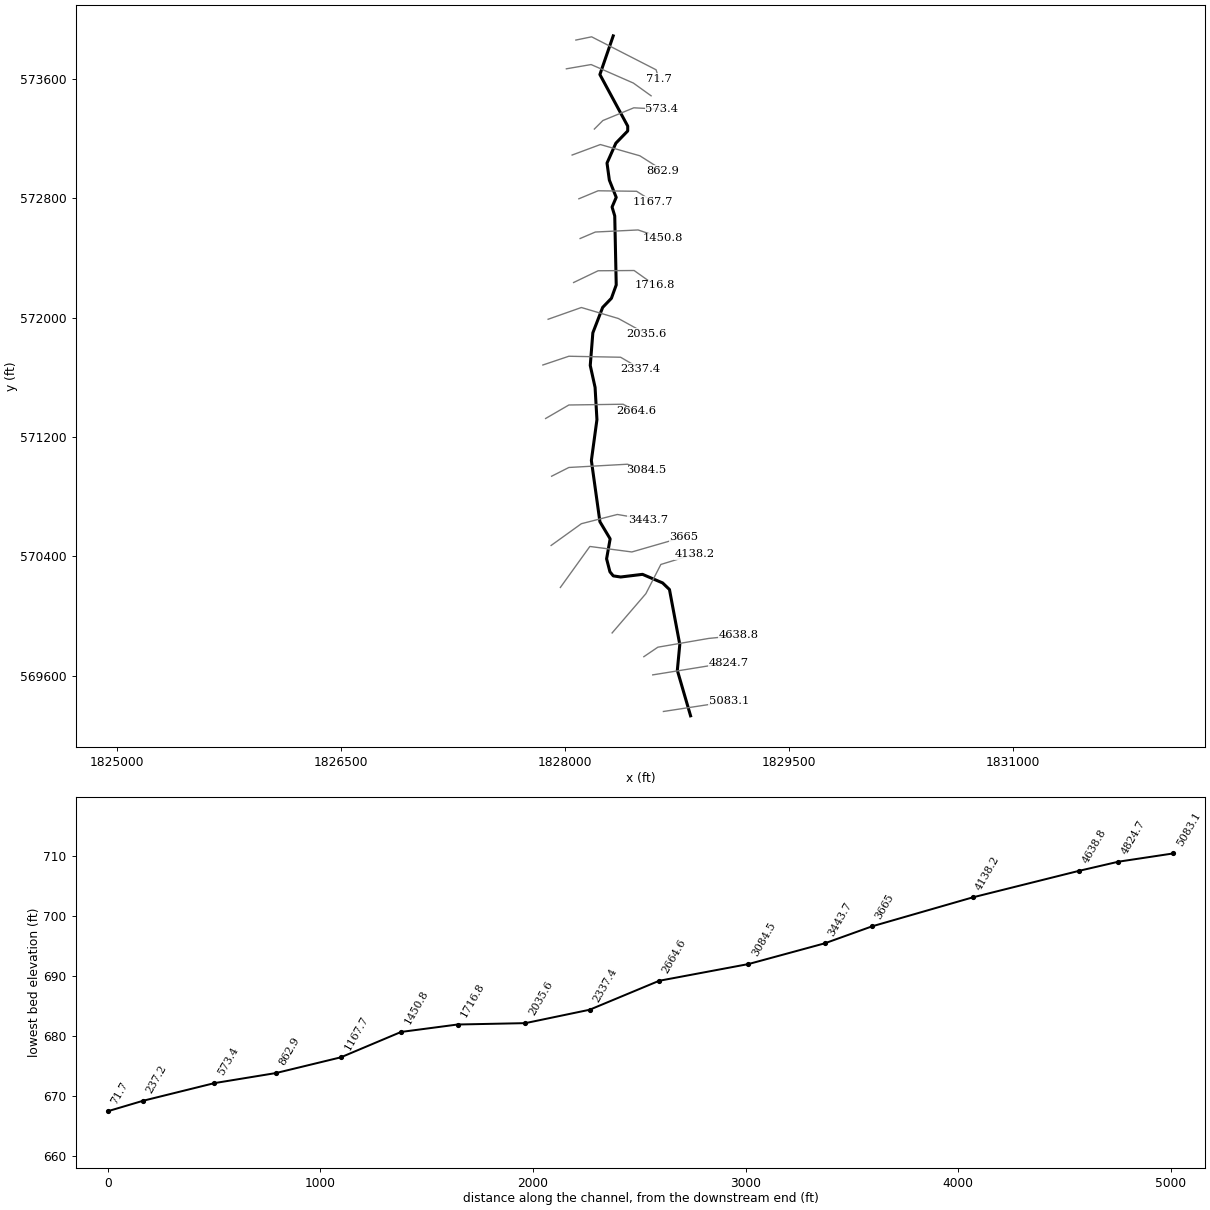
--- ColemanFrk.prj (project) ---

Proj Title=ColemanFrk
Current Plan=p01
Default Exp/Contr=0,0
English Units
Geom File=g01
Flow File=f01
Plan File=p01
BEGIN DESCRIPTION:
AMEC Environment & Infrastructure, 2013
Projection: NAD 1983 State Plane West Virginia South FIPS 4702 (US Feet)
Vertical Datum: NAVD 1988
END DESCRIPTION:
DSS Export Rating Curves= 0
DSS Export Rating Curve Sorted= 0
DSS Export Volume Flow Curves= 0
DXF OffsetX= 0
DXF OffsetY= 0
DXF ScaleX= 0
DXF ScaleY= 0

--- ColemanFrk.p01 (plan) ---

Plan Title=Floodplain
Program Version=4.00
Geom File=g01
Flow File=f01
K Sum by GR=0
Std Step Tol=0.01
Critical Tol=0.01
Num of Std Step Trials=20
Max Error Tol=0.3
Flow Tol Ratio=0.001
Split Flow NTrial=30
Split Flow Tol=0.02
Split Flow Ratio=0.02
Log Output Level=0
Friction Slope Method=1
Unsteady Friction Slope Method=2
Unsteady Bridges Friction Slope Method=1
Global Log Level=0
CheckData=False
Run HTab=0
Run UNet=0
Run PostProcess=0
UNET Theta=0
UNET Theta Warmup=0
UNET ZTol=0
UNET ZSATol=0
UNET MxIter=0
UNET MaxInSteps=0
UNET DtIC=0
UNET DtMin=0
UNET MaxCRTS=0
UNET WFStab=0
UNET SFStab=0
UNET WFX=0
UNET SFX=0
UNET DSS MLevel=0
UNET DZMax Abort=0
UNET Convert EG Bridges=0
UNET Use Existing IB Tables=0
UNET Froude Limit=0
UNET Froude Power=0
Write IC File=0
Echo Input=False
Echo Output=False
Write Detailed=0

--- ColemanFrk.f01 (steady flow) ---

Flow Title=NFF Regression Equation
Program Version=4.00
Number of Profiles=1
Profile Names=P100yr
River Rch & RM=ColemanFrk,Main      ,5083.1
917.8380
River Rch & RM=ColemanFrk,Main      ,3665
1010.187
River Rch & RM=ColemanFrk,Main      ,237.2
1066.657
River Rch & RM=ColemanFrk,Main      ,71.7
1068.658
Boundary for River Rch & Prof#=ColemanFrk,Main      ,1
Up Type=0
Dn Type=3
Dn Slope=0.00948

--- ColemanFrk.g01 (geometry) ---

Geom Title=USGS 3m DEM
Program Version=4.10

River Reach=ColemanFrk      ,Main
Reach XY= 30
     1828841.245      569331.386     1828752.529      569636.247
     1828768.951      569809.298     1828699.836      570177.691
     1828653.984      570221.845      1828519.22      570279.388
      1828373.01      570261.616      1828323.28      570269.073
       1828300.9      570296.423     1828278.518      570383.449
      1828302.36       570517.14      1828233.75      570632.095
     1828176.543      571042.362     1828213.828      571315.877
     1828201.386        571532.2     1828169.055      571678.901
      1828186.45      571897.712     1828252.204      572067.965
     1828310.764      572128.961     1828343.084      572218.476
     1828333.117      572680.961     1828315.212      572740.636
     1828343.057      572805.286     1828296.972      572921.101
     1828281.351      573035.205     1828340.555      573168.312
     1828420.118       573250.37     1828420.117      573282.694
     1828233.615      573628.307     1828322.907      573887.303

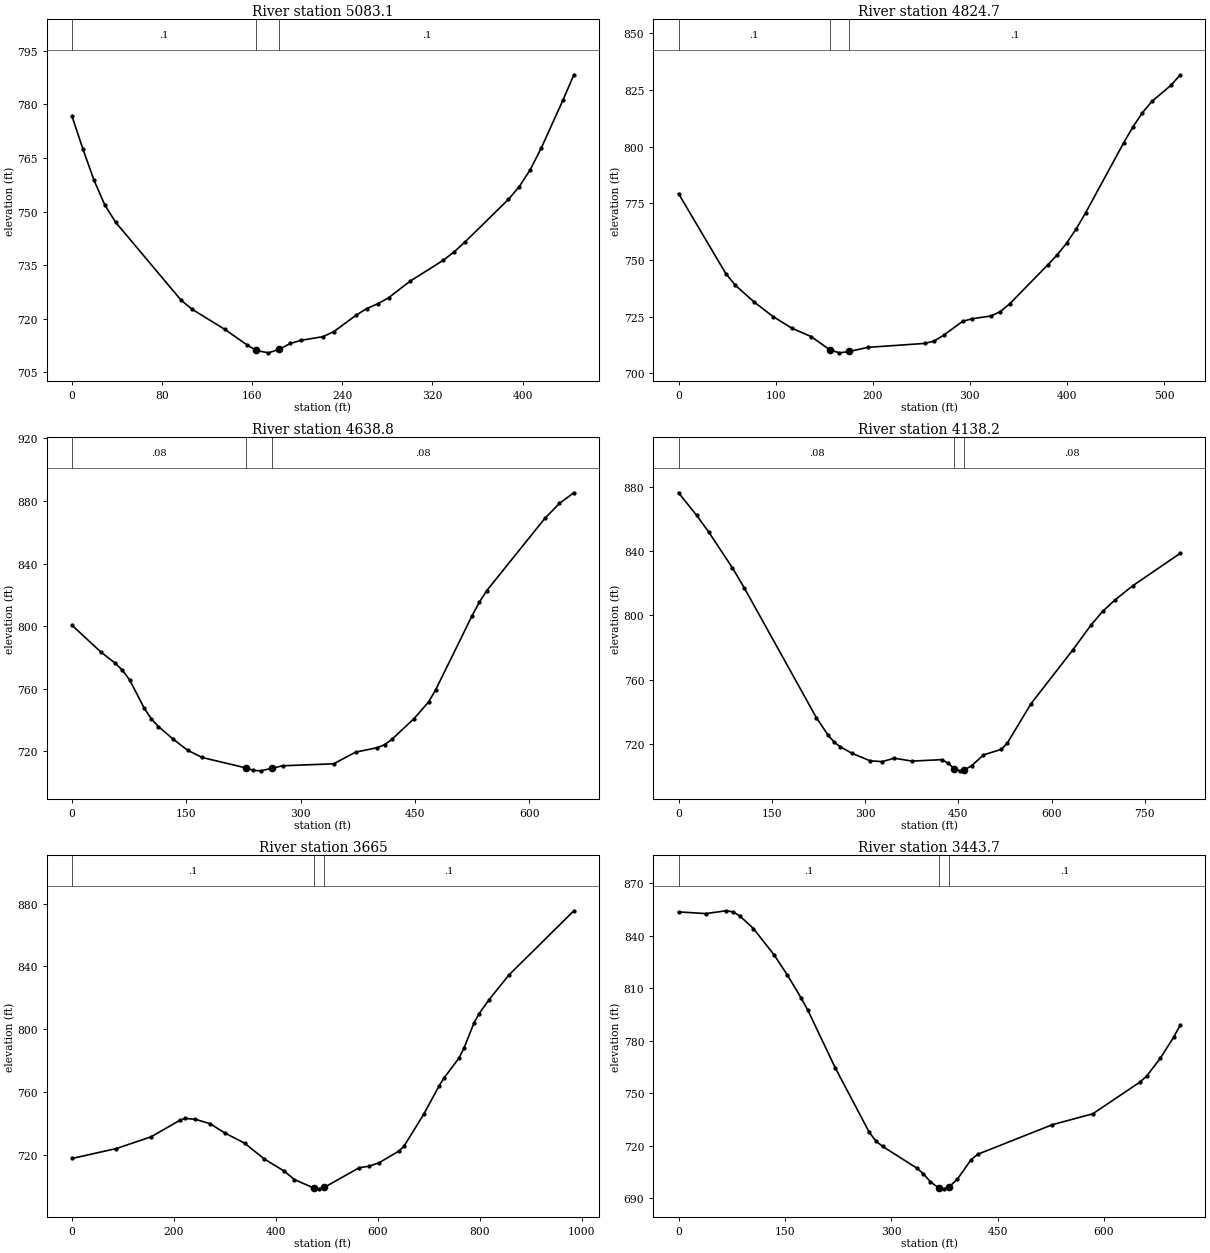
Type RM Length L Ch R = 1 ,5083.1  ,258.3,258.4,258.5
XS GIS Cut Line= 2
       1828659.3      569360.509     1829099.838      569427.784
#Sta/Elev= 30
       0  776.63     9.7  767.45    19.4  758.84    29.1  751.82    38.8  746.97
    96.9  725.15   106.6  722.64   135.6  717.02     155  712.74   163.5  711.11
   174.4  710.44   184.1  711.44   193.8  713.07   203.4  713.95   222.8  714.97
   232.5  716.39   251.9  720.91   261.6  722.81   271.3  724.17     281  725.85
   300.3  730.53   329.4  736.32   339.1  738.66   348.8  741.45   387.5  753.42
   397.2  757.02   406.9  761.76   416.6  767.76     436  781.27   445.6  788.31
#Mann= 3 , 0 , 0
       0      .1       0   163.5    .045       0   184.1      .1       0
Bank Sta=163.5,184.1
XS Rating Curve= 0 ,0
Exp/Cntr=0.3,0.1

Type RM Length L Ch R = 1 ,4824.7  ,185.6,186,186.3
XS GIS Cut Line= 2
     1828587.686      569605.735     1829097.668        569688.2
#Sta/Elev= 30
       0  779.26    48.7  743.98    58.5  738.85      78  731.41    97.5  725.01
     117  719.85   136.5  716.23     156  710.31   165.7  709.06     176  709.67
     195  711.48   253.4  713.21   263.2  714.28   272.9   716.8   292.4  722.93
   302.2  724.09   321.7  725.31   331.4  727.28   341.2  730.79   380.1  747.83
   389.9  752.31   399.6  757.46   409.4  763.72   419.1   770.8   458.1  801.53
   467.9  808.75   477.6  814.96   487.4  819.96   506.9  827.01   516.6  831.67
#Mann= 3 , 0 , 0
       0      .1       0     156    .045       0     176      .1       0
Bank Sta=156,176
XS Rating Curve= 0 ,0
Exp/Cntr=0.3,0.1

Type RM Length L Ch R = 1 ,4638.8  ,479.5,500.5,521.6
XS GIS Cut Line= 4
     1828528.196      569727.648     1828621.983       569791.29
     1828961.963      569849.907     1829161.261      569870.004
#Sta/Elev= 30
       0  800.54    37.8  783.49    56.7  776.28    66.1  771.86    75.6  765.62
    94.4  747.87   103.9  740.85   113.3  735.87   132.5  727.85   151.7  720.69
   170.8  716.06   228.3  709.38   237.9  707.84   247.5  707.53  262.42709.1734
   276.3  710.76   343.3  712.03   372.1  719.46   400.8  722.37   410.4  724.29
     420  727.76   448.8   740.9   467.9  751.51   477.4  759.51   525.1  806.75
   534.6   815.4   544.2  822.66   620.5  868.88   639.6  878.47   658.6  885.26
#Mann= 3 , 0 , 0
       0     .08       0   228.3    .045       0  262.42     .08       0
Bank Sta=228.3,262.42
XS Rating Curve= 0 ,0
Exp/Cntr=0.3,0.1

Type RM Length L Ch R = 1 ,4138.2  ,501.5,473.2,444.7
XS GIS Cut Line= 4
     1828315.499      569886.752     1828541.594      570149.692
      1828642.08      570345.641     1828871.525      570415.982
#Sta/Elev= 30
       0  876.49    28.9  862.51    48.2  852.23    86.7  829.64     106     817
   221.6  736.32   240.8  725.18   250.4     721   260.1   718.1   279.4  713.95
   308.2  709.35   327.5  708.84   346.8  710.97   375.5  709.18   423.4  710.07
     433  707.97   443.8  704.44   452.1   703.1   458.8  703.53   471.2  706.22
   490.4  713.03   519.1  716.51   528.7   720.4     567  745.04   634.2  778.55
     663  793.85   682.2  802.59   701.4  809.47   730.2  818.45     807   838.8
#Mann= 3 , 0 , 0
       0     .08       0   443.8    .045       0   458.8     .08       0
Bank Sta=443.8,458.8
XS Rating Curve= 0 ,0
Exp/Cntr=0.3,0.1

Type RM Length L Ch R = 1 ,3665    ,212.2,221.4,230.2
XS GIS Cut Line= 4
      1827968.82      570191.562     1828166.444      570466.225
     1828447.806       570429.38      1828796.16      570529.867
#Sta/Elev= 30
       0  717.63      87  723.94   154.7  731.38   212.7  742.12   222.4   743.1
   241.7  742.61   270.7  739.76   299.7  733.86   338.4  727.39   377.5  717.24
   416.6   709.5   436.2  704.17   475.4  698.67   485.2  698.27   494.9   699.2
   563.4  711.71     583  712.71   602.6  714.91   641.7  722.38   651.5  725.52
   690.7  746.12   720.1  763.82   729.9  768.87   759.3  781.59   769.1  787.92
   788.7  803.93   798.5  809.76   818.1  818.69   857.3   834.5   984.7  875.39
#Mann= 3 , 0 , 0
       0      .1       0   475.4    .045       0   494.9      .1       0
Bank Sta=475.4,494.9
XS Rating Curve= 0 ,0
Exp/Cntr=0.3,0.1

Type RM Length L Ch R = 1 ,3443.7  ,363.5,359.1,354.7
XS GIS Cut Line= 4
     1827906.853      570472.924     1828109.501       570618.63
     1828350.669      570680.596     1828556.667      570645.426
#Sta/Elev= 30
       0  853.54    38.4  852.57    67.2  854.17    76.8  853.56    86.4  851.23
   105.6  844.04   134.4  829.19   153.6  817.43   172.8  804.46   182.4  797.36
   220.8  764.68   268.8  727.84   278.3  722.76   287.9  719.64   335.8  707.34
   345.4  704.02   354.9  699.56   366.8  696.02   374.1  695.45   381.8  696.64
   393.2  700.98   412.4  712.01     422  715.19   527.1  732.06   584.1  738.28
   650.6  756.37   660.1  759.81   679.1  769.85   698.1   781.9   707.6  789.03
#Mann= 3 , 0 , 0
       0      .1       0   366.8    .045       0   381.8      .1       0
Bank Sta=366.8,381.8
XS Rating Curve= 0 ,0
Exp/Cntr=0.3,0.1

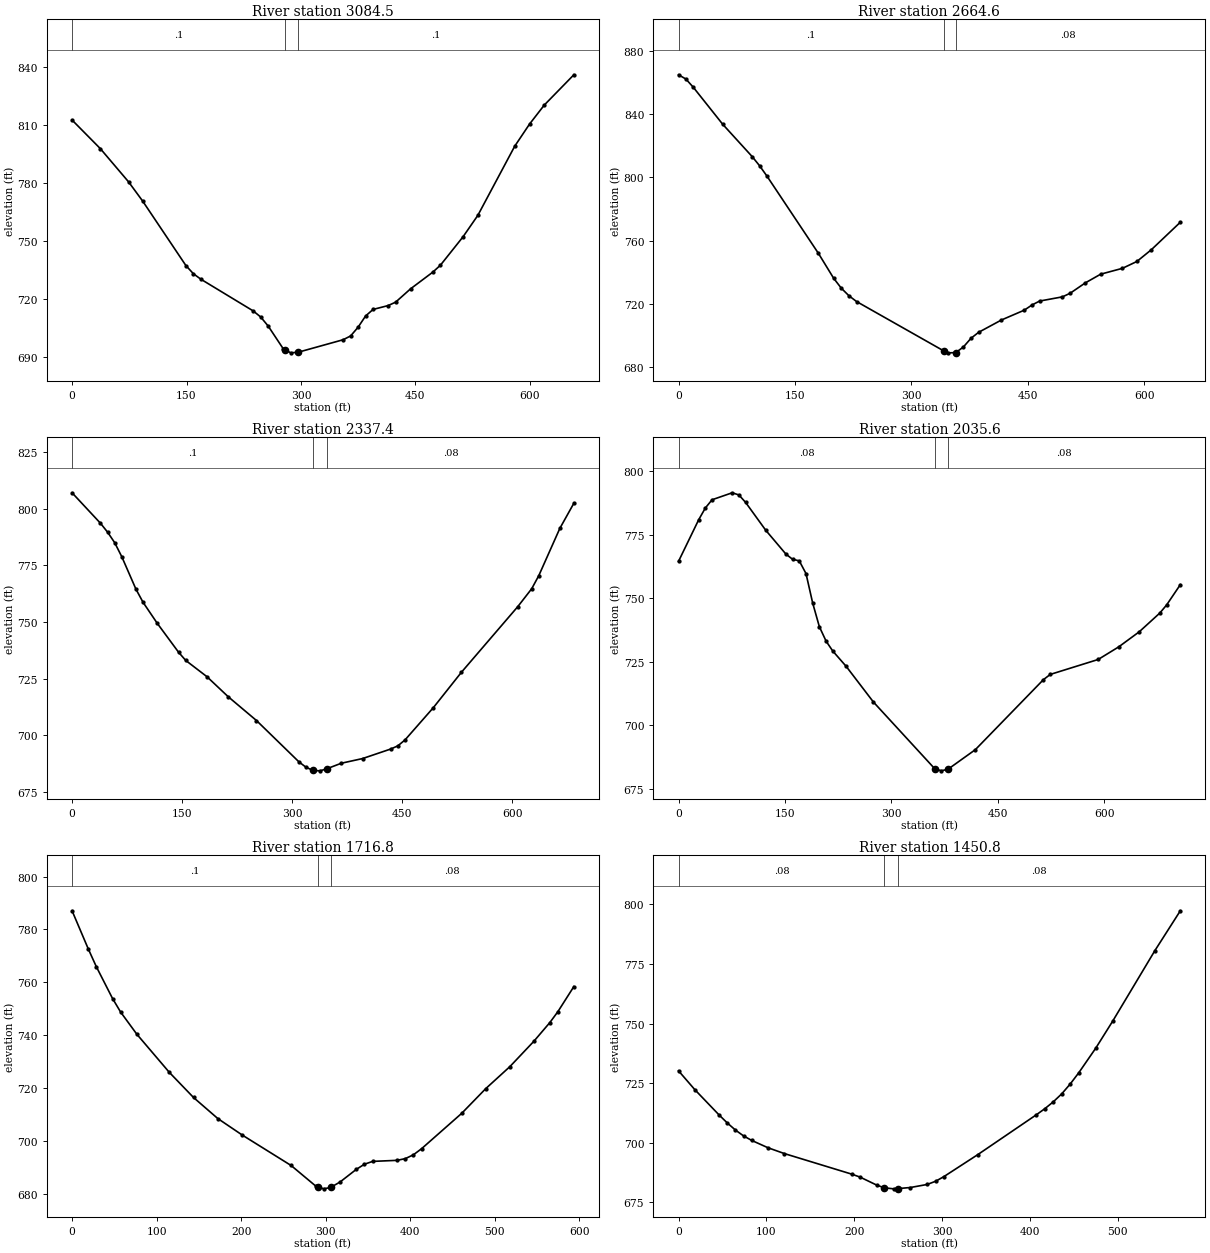
Type RM Length L Ch R = 1 ,3084.5  ,420.9,420,419
XS GIS Cut Line= 4
     1827910.203      570936.837     1828025.763      570995.454
      1828417.66      571017.227     1828546.618      570975.357
#Sta/Elev= 30
       0  812.41      37  797.64      74  780.46    92.6  770.45   149.2  737.14
     159  732.91   168.8  730.08   237.5  713.65   247.3   710.5   257.1  705.81
   276.8  694.08   279.7  693.46   286.6  691.99   296.4  692.31   355.3  698.77
   365.1  700.73   374.9  705.25   384.7  711.04   394.5  714.44   414.1  716.42
     424  718.18   443.6  725.08     473  733.79   482.8  737.32   512.3  751.94
   531.8  763.07   580.2  798.88   599.6  810.31   618.9  820.14   657.7  835.82
#Mann= 3 , 0 , 0
       0      .1       0   279.7    .045       0   296.4      .1       0
Bank Sta=279.7,296.4
XS Rating Curve= 0 ,0
Exp/Cntr=0.3,0.1

Type RM Length L Ch R = 1 ,2664.6  ,328.1,327.2,326.1
XS GIS Cut Line= 4
     1827870.008      571323.711     1828025.763      571414.149
     1828389.189      571419.173     1828479.627      571370.604
#Sta/Elev= 30
       0  864.91     9.5  862.21      19  857.02    56.9  833.63    94.8  813.22
   104.3  807.47   113.8  800.93   180.1  752.09   199.8   736.3   209.6  730.06
   219.4  725.29   229.2  721.64  341.81690.3481   347.1   689.2   356.9  689.32
   366.8  692.88   376.6  698.38   386.4  702.16   415.9  709.97   445.3  716.18
   455.2  719.45     465  721.92   494.4  724.58   504.3  726.85   523.9  733.42
   543.6   738.9   571.6   742.6   590.2  746.92   608.9  754.37   646.2  771.73
#Mann= 3 , 0 , 0
       0      .1       0  341.81    .045       0   356.9     .08       0
Bank Sta=341.81,356.9
XS Rating Curve= 0 ,0
Exp/Cntr=0.3,0.1

Type RM Length L Ch R = 1 ,2337.4  ,307.8,301.7,295.6
XS GIS Cut Line= 4
     1827851.586      571682.113     1828025.763       571740.73
     1828372.441      571734.031     1828504.749      571656.991
#Sta/Elev= 30
       0  806.97    38.7  793.53    48.4   789.6      58     785    67.7   778.8
      87  764.48    96.7  758.68   116.1  749.39   145.1  736.66   154.8  733.06
   183.8  725.87   212.7  717.05   251.2  706.56     309  688.35   318.6  685.97
   328.2  684.55   337.9  684.37   347.5  685.34   366.8  687.72   395.7  689.78
   434.2     694   443.8  695.39   453.5  697.97     492  712.16   530.5  727.86
   607.1  756.73   626.2  764.68   635.8  770.42   664.5  791.27   683.6  802.36
#Mann= 3 , 0 , 0
       0      .1       0   328.2    .045       0   347.5     .08       0
Bank Sta=328.2,347.5
XS Rating Curve= 0 ,0
Exp/Cntr=0.3,0.1

Type RM Length L Ch R = 1 ,2035.6  ,312,318.9,325.5
XS GIS Cut Line= 4
     1827886.756      571988.597     1828109.501      572067.312
     1828357.368      571993.621     1828543.269       571891.46
#Sta/Elev= 30
       0  764.47    28.4  780.81    37.8  785.43    47.2  788.65    75.6   791.4
      85  790.56    94.5  787.62   122.8   776.7   151.2  767.34   160.6  765.28
   170.1  764.65   179.6  759.65     189  748.08   198.4  738.79   207.9   733.1
   217.3  729.22   236.2  723.19   274.6  709.17   360.8  683.02   370.3  682.14
   379.9  682.82   418.2  690.46   514.1  717.97   523.8  720.03   591.2  725.89
   620.2  730.85   649.1  736.77     678  744.11   687.7  747.32     707   755.3
#Mann= 3 , 0 , 0
       0     .08       0   360.8    .045       0   379.9     .08       0
Bank Sta=360.8,379.9
XS Rating Curve= 0 ,0
Exp/Cntr=0.3,0.1

Type RM Length L Ch R = 1 ,1716.8  ,265,265.9,266.9
XS GIS Cut Line= 4
     1828057.583      572234.789     1828221.711      572313.504
     1828462.879      572315.178     1828601.886      572216.367
#Sta/Elev= 30
       0  787.07    19.2  772.63    28.7  765.93    47.9  753.89    57.5  748.75
    76.6   740.4     115  725.99   143.7  716.46   172.4  708.51   201.3  702.27
   259.2  690.74   288.1  683.03   290.9  682.71   297.8  681.91   305.9  682.43
   317.1  684.49   336.4  689.29     346  691.22   355.7  692.29   384.6  692.69
   394.3  693.33   403.9  694.78   413.6  697.09   461.1  710.47   489.5   719.8
     518   728.1   546.4  737.69   565.3  744.76   574.8  748.87   593.8  758.41
#Mann= 3 , 0 , 0
       0      .1       0   290.9    .045       0   305.9     .08       0
Bank Sta=290.9,305.9
XS Rating Curve= 0 ,0
Exp/Cntr=0.3,0.1

Type RM Length L Ch R = 1 ,1450.8  ,287.1,283.1,280.7
XS GIS Cut Line= 4
     1828101.128       572529.55     1828203.289      572573.094
     1828489.572      572586.954     1828653.804      572531.225
#Sta/Elev= 30
       0  730.18    18.5   722.3    46.3  711.61    55.5  708.31    64.8  705.32
      74  702.88    83.3  700.98   101.8  697.91   120.6  695.45     197  686.85
   206.6   685.6   225.7  682.21   234.3   681.1   244.8  680.67   249.3  680.76
   263.9  681.23     283  682.51   292.6  683.85   302.1  685.82   340.4  694.98
   407.3  711.76   416.9   714.3   426.6   717.2   436.2  720.55   445.8  724.66
   455.5  729.36   474.8  739.67     494  750.95   542.2  780.65   571.1  797.33
#Mann= 3 , 0 , 0
       0     .08       0   234.3    .045       0   249.3     .08       0
Bank Sta=234.3,249.3
XS Rating Curve= 0 ,0
Exp/Cntr=0.3,0.1

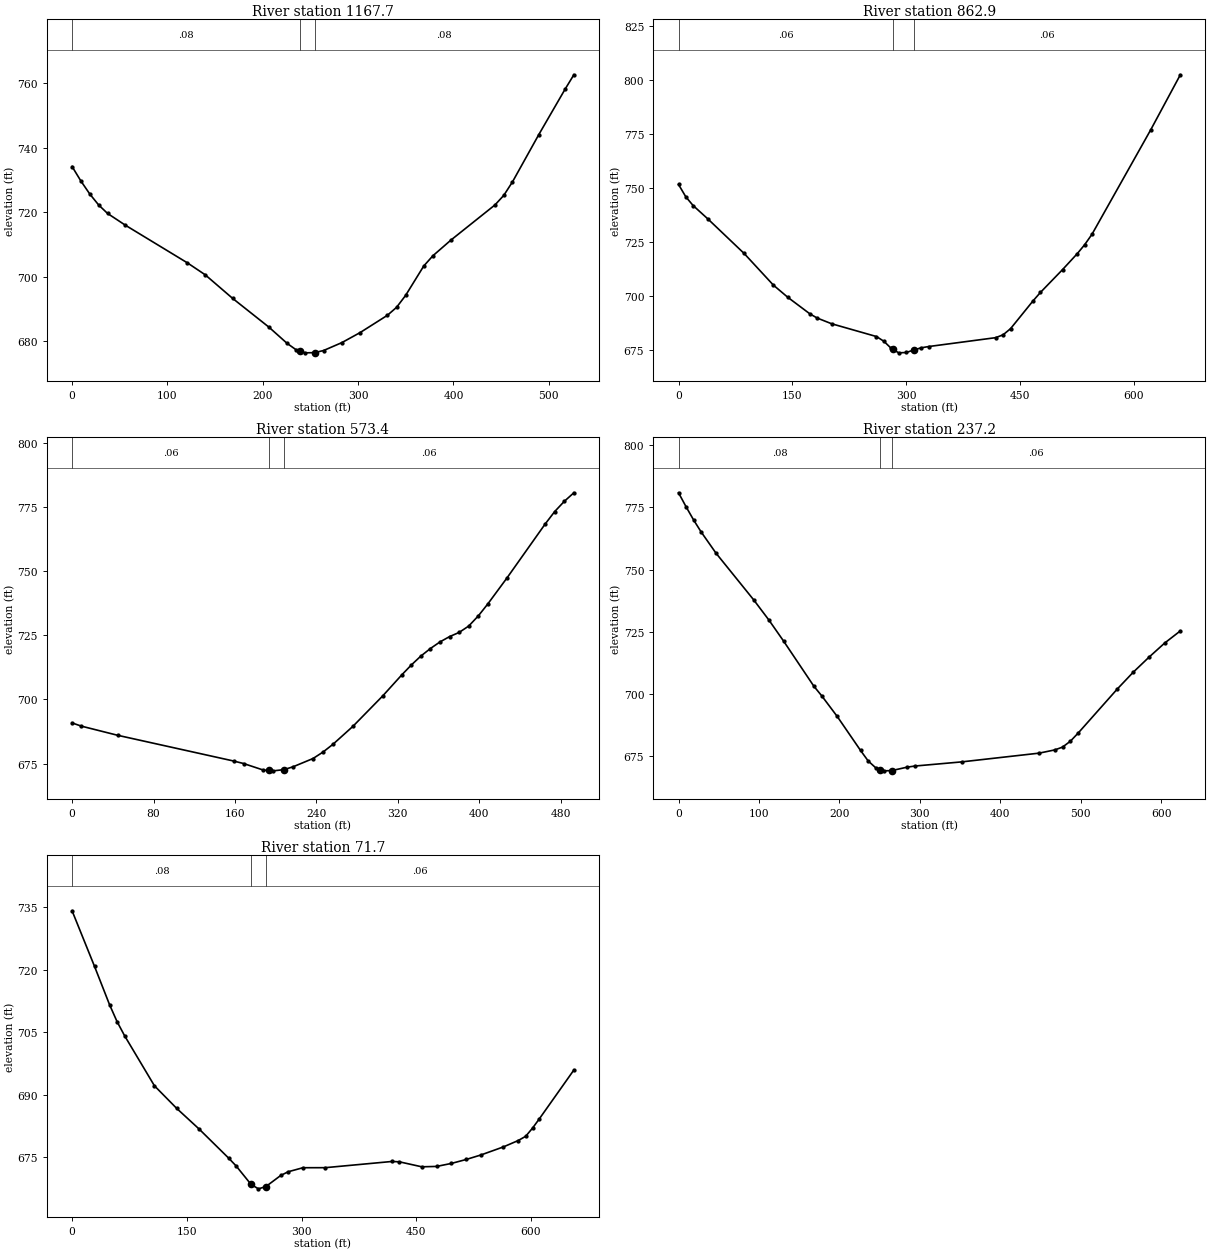
Type RM Length L Ch R = 1 ,1167.7  ,309.1,304.8,300.3
XS GIS Cut Line= 4
     1828092.754      572795.839     1828221.711      572849.432
     1828479.627      572846.083     1828588.488      572777.417
#Sta/Elev= 30
       0  734.15     9.3  729.64    18.6  725.62    27.9  722.23    37.2  719.62
    55.9  715.97     121   704.3   139.6  700.62   168.3  693.33   206.5  684.39
   225.6  679.36   235.2  677.34   239.3  676.95   244.7  676.44   254.3   676.5
   263.8  677.16     283  679.61   302.1  682.71   330.7  688.06   340.3  690.52
   349.8  694.21   368.9  703.35   378.5  706.52   397.6  711.42   443.6  722.26
   452.8  725.21   461.9  729.38   489.5  744.02   517.1   758.1   526.3  762.56
#Mann= 3 , 0 , 0
       0     .08       0   239.3    .045       0   254.3     .08       0
Bank Sta=239.3,254.3
XS Rating Curve= 0 ,0
Exp/Cntr=0.3,0.1

Type RM Length L Ch R = 1 ,862.9   ,274.2,289.5,304.4
XS GIS Cut Line= 4
     1828047.535      573088.925     1828236.784      573159.266
     1828501.399      573083.901     1828657.153      572985.089
#Sta/Elev= 30
       0   751.8     9.6  746.08    19.2  742.05    38.5   735.9    86.5  719.84
     125   705.2   144.2   699.5   173.1  691.89   182.7  689.95   201.9  687.28
   260.9  681.37   270.7  679.18   280.5  675.85   282.8  675.37   290.3  673.82
   300.2  673.98     310  675.12   319.8  676.14   329.6  676.73   418.1  680.85
   427.9  682.18   437.7  685.02   467.2  697.83     477  701.77   506.2  712.36
   525.6  719.74   535.3  723.86     545  728.71   622.7  777.26   661.5  802.61
#Mann= 3 , 0 , 0
       0     .06       0   282.8    .045       0     310     .06       0
Bank Sta=282.8,310
XS Rating Curve= 0 ,0
Exp/Cntr=0.3,0.1

Type RM Length L Ch R = 1 ,573.4   ,354.6,336.3,317.9
XS GIS Cut Line= 4
      1828196.59      573263.102     1828253.532      573320.045
     1828461.205      573405.458      1828648.78      573395.409
#Sta/Elev= 30
       0  690.85       9   689.6    44.7  686.02   158.6  675.98   168.4     675
   187.9  672.44   193.2  672.28   197.7  672.14   208.2  672.61   217.2  673.74
   236.7  676.95   246.5  679.47   256.3  682.51   275.8  689.48   305.1  701.36
   323.9   709.6   333.3  713.47   342.6  716.93     352  719.88   361.4  722.45
   370.8  724.53   380.2  726.16   389.6  728.64     399  732.59   408.4  737.29
   427.2  747.42   464.8  768.52   474.1  773.34   483.5  777.32   492.9  780.66
#Mann= 3 , 0 , 0
       0     .06       0   193.2    .045       0   208.2     .06       0
Bank Sta=193.2,208.2
XS Rating Curve= 0 ,0
Exp/Cntr=0.3,0.1

Type RM Length L Ch R = 1 ,237.2   ,167,165.5,164.1
XS GIS Cut Line= 4
     1828009.015      573666.723     1828174.818      573695.195
     1828457.855      573571.261     1828576.764      573485.847
#Sta/Elev= 30
       0  780.87     9.4  775.23    18.7  769.97      28  765.18    46.7  756.56
    93.5  737.82   112.2   729.8   130.8  721.19   168.2  703.17   177.9  699.34
   197.2  691.04   226.2  677.38   235.7  673.15   245.5  670.28   250.7  669.69
   255.1  669.19   264.8  669.28   284.1  670.67   293.8  671.12   351.7  672.78
   448.2   676.3   467.6   677.6   477.2  678.72     487   681.1   496.7  684.38
   545.5  702.14   565.1  708.81   584.6  714.82   604.1   720.5   623.6  725.39
#Mann= 3 , 0 , 0
       0     .08       0   250.7    .045       0   264.8     .06       0
Bank Sta=250.7,264.8
XS Rating Curve= 0 ,0
Exp/Cntr=0.3,0.1

Type RM Length L Ch R = 1 ,71.7    ,69.9,71.7,73.4
XS GIS Cut Line= 4
     1828072.656      573859.323     1828178.167      573881.095
      1828610.26      573660.024     1828628.682      573599.732
#Sta/Elev= 30
       0  734.08    29.4  720.74      49  711.58    58.8  707.53    68.6  704.16
   107.7  692.14   136.9  686.71     166   681.8   204.8   674.8   214.5  672.94
   233.9  668.54   243.6  667.45   253.3  667.98   272.8  670.65   282.5  671.54
   301.9  672.51     331  672.52   418.4  674.01   428.1  673.92   457.2  672.73
   476.6  672.82     496  673.54   515.4  674.49   534.8  675.58     564   677.5
   583.4  679.03   593.1  680.04   602.1  682.01   611.1  684.26   656.1  695.92
#Mann= 3 , 0 , 0
       0     .08       0   233.9    .045       0   253.3     .06       0
Bank Sta=233.9,253.3
XS Rating Curve= 0 ,0
Exp/Cntr=0.3,0.1

Chan Stop Cuts=-1
Use User Specified Reach Order=0
Composite Channel Slope=5